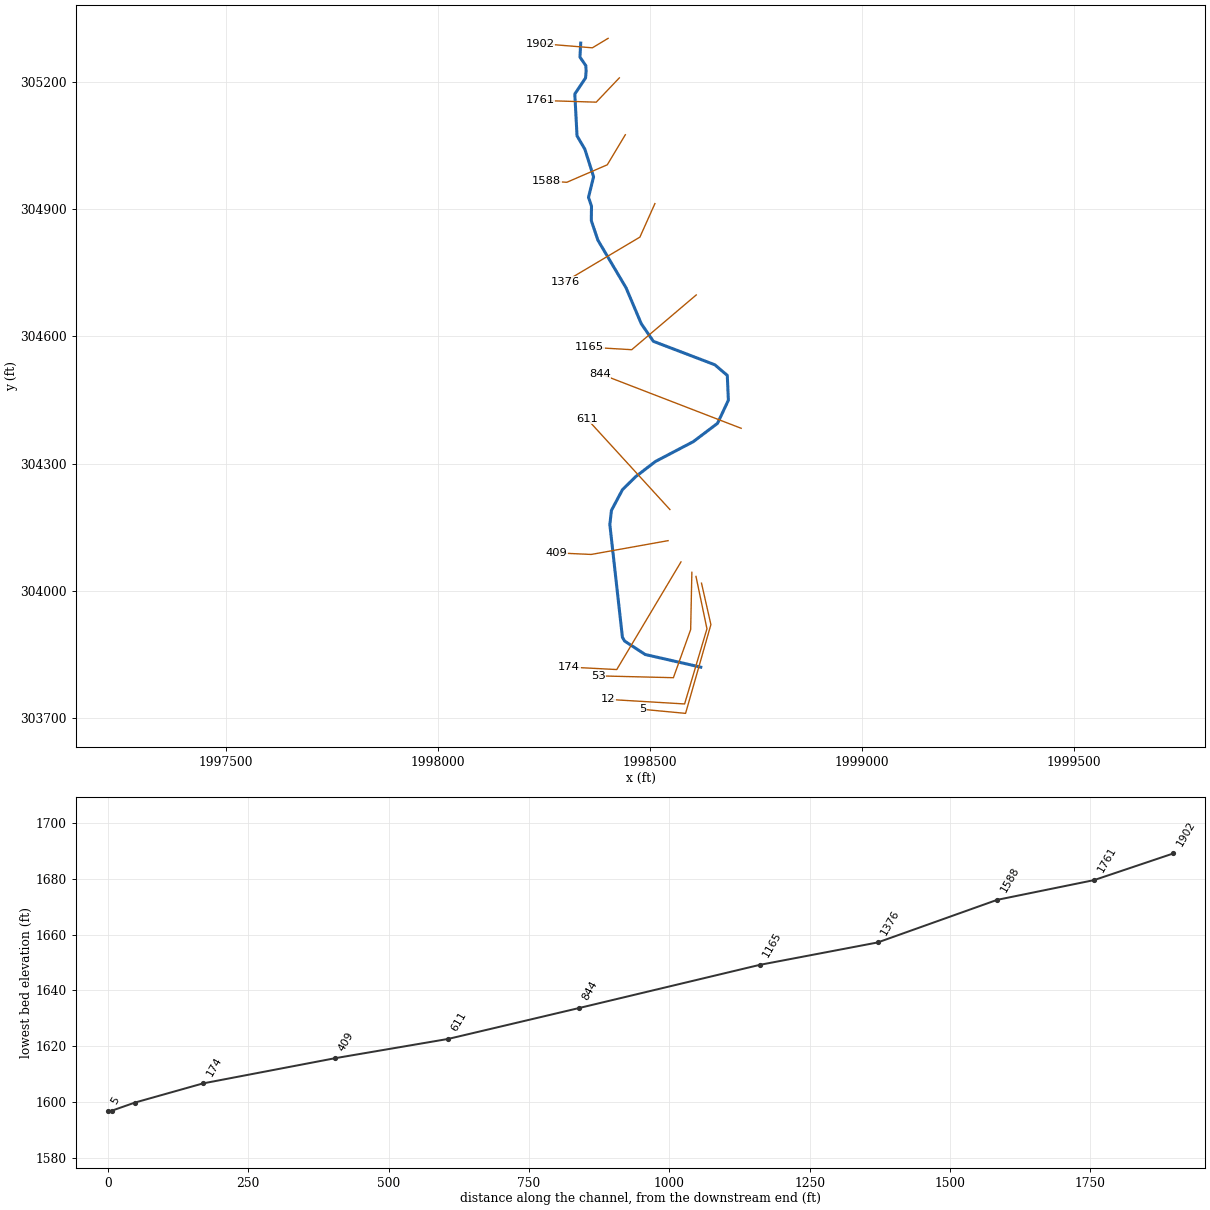
--- LFMEADOWCK.prj (project) ---

Proj Title=LFMEADOWCK
Current Plan=p01
Default Exp/Contr=0,0
English Units
Geom File=g01
Flow File=f01
Plan File=p01
BEGIN DESCRIPTION:
Stream Name: Lefthand Fork Meadow Creek
Flood Zone: Approximate
Summers County, West Virginia
HEC-RAS Version: 5.0.7
Hydrology Method:
regression
Model Notes:
END DESCRIPTION:
DSS Export Rating Curves= 0
DSS Export Rating Curve Sorted= 0
DSS Export Volume Flow Curves= 0
DXF OffsetX= 0
DXF OffsetY= 0
DXF ScaleX= 0
DXF ScaleY= 0

--- LFMEADOWCK.p01 (plan) ---

Plan Title=Floodplain
Program Version=5.07
Short Identifier=Floodplain
Geom File=g01
Flow File=f01
Subcritical Flow
K Sum by GR= 0
Std Step Tol= 0.01
Critical Tol= 0.01
Num of Std Step Trials= 20
Max Error Tol= 0.3
Flow Tol Ratio= 0.001
Split Flow NTrial= 30
Split Flow Tol= 0.02
Split Flow Ratio= 0.02
Log Output Level= 0
Friction Slope Method= 1
Unsteady Friction Slope Method= 2
Unsteady Bridges Friction Slope Method= 1
Parabolic Critical Depth
Global Vel Dist= 0 , 0 , 0
Global Log Level= 0
CheckData=True
Encroach Param=-1 ,0,0, 0
Mapping Interval=1HOUR
Computation Time Step Use Courant=        0
Computation Time Step Use Time Series=    0
Computation Time Step Count To Double=0
Computation Time Step Max Doubling=0
Computation Time Step Max Halving=0
Computation Time Step Residence Courant=0
Run HTab= 0
Run UNet= 0
Run Sediment= 0
Run PostProcess= 0
Run WQNet= 0
Run RASMapper= 0
UNET Theta= 0
UNET Theta Warmup= 0
UNET ZTol= 0
UNET ZSATol= 0
UNET MxIter= 0
UNET Max Iter WO Improvement= 0
UNET MaxInSteps= 0
UNET DtIC= 0
UNET DtMin= 0
UNET MaxCRTS= 0
UNET WFStab= 0
UNET SFStab= 0
UNET WFX= 1
UNET SFX= 1
UNET 1D Methodology=Finite Difference
UNET DSS MLevel= 1
UNET Pardiso=0
UNET DZMax Abort= 0
UNET Use Existing IB Tables= 0
UNET Froude Reduction=False
UNET Froude Limit= 0
UNET Froude Power= 0
UNET D1 Cores= 0
UNET D2 Coriolis=0
UNET D2 Cores= 0
UNET D2 Theta= 1
UNET D2 Theta Warmup= 1
UNET D2 Z Tol= 0.01
UNET D2 Volume Tol= 0.01
UNET D2 Max Iterations= 20
UNET D2 Equation= 0
UNET D2 RampUpFraction=0.1
UNET D2 TimeSlices= 1
UNET D2 BCVolumeCheck=0
UNET D1D2 MaxIter= 0
UNET D1D2 ZTol=0.01
UNET D1D2 QTol=0.1
UNET D1D2 MinQTol=1
Write IC File= 0
Write IC File at Fixed DateTime=0
Write IC File at Sim End=0
Echo Input=False
Echo Parameters=False
Echo Output=False
Write Detailed= 0
HDF Write Warmup=0
HDF Write Time Slices=0
HDF Flush=0
HDF Face Node Velocities=0
HDF Compression= 1
HDF Chunk Size= 1
HDF Spatial Parts= 1
HDF Use Max Rows=0
HDF Fixed Rows= 1
Calibration Method= 0
Calibration Iterations= 20
Calibration Max Change=0.05
Calibration Tolerance=0.2
Calibration Maximum=1.5
Calibration Minimum=0.5
Calibration Optimization Method= 1
WQ AD Non Conservative
WQ ULTIMATE=-1
WQ Max Comp Step=1HOUR
WQ Output Interval=15MIN
WQ Output Selected Increments= 0
WQ Output face flow=0
WQ Output face velocity=0
WQ Output face area=0
WQ Output face dispersion=0
WQ Output cell volume=0
WQ Output cell surface area=0
WQ Output cell continuity=0
WQ Output cumulative cell continuity=0
WQ Output face conc=0
WQ Output face dconc_dx=0
WQ Output face courant=0
WQ Output face peclet=0
WQ Output face adv mass=0
WQ Output face disp mass=0
WQ Output cell mass=0
WQ Output cell source sink temp=0
WQ Output nsm pathways=0
WQ Output nsm derived pathways=0
WQ Output MaxMinRange=-1
WQ Daily Max Min Mean=-1
WQ Daily Range=0
WQ Daily Time=0
WQ Create Restart=0
WQ Fixed Restart=0
WQ System Summary=0
WQ Write To DSS=0
WQ Use Fixed Temperature=0
Sorting and Armoring Iterations= 10
XS Update Threshold= 0.02
Bed Roughness Predictor= 0
Hydraulics Update Threshold= 0.02
Energy Slope Method= 1
Volume Change Method= 1
Sediment Retention Method= 0
XS Weighting Method= 0
Number of US Weighted Cross Sections= 1
Number of DS Weighted Cross Sections= 1
Upstream XS Weight=0
Main XS Weight=1
Downstream XS Weight=0
Number of DS XS's Weighted with US Boundary= 1
Upstream Boundary Weight= 1
Weight of XSs Associated with US Boundary= 0
Number of US XS's Weighted with DS Boundary= 1
Downstream Boundary Weight= 0.5
Weight of XSs Associated with DS Boundary= 0.5
Percentile Method= 0
Sediment Output Level= 3
Mass or Volume Output= 0
Output Increment Type= 1
Profile and TS Output Increment= 1
XS Output Flag= 0
XS Output Increment= 10
Write Gradation File= 0
Read Gradation Hotstart= 0
Write HDF5 File= 1
Write Binary Output= 1
Write DSS Sediment File= 0
SV Curve= 0
Specific Gage Flag= 0

--- LFMEADOWCK.f01 (steady flow) ---

Flow Title=Flows
Program Version=5.07
Number of Profiles= 6
Profile Names=01pct,10pct,04pct,02pct,0_2pct,01plus
River Rch & RM=LFMEADOWCK,Main            ,1902
    1092     591     777     929    1507    1615
Boundary for River Rch & Prof#=LFMEADOWCK,Main            , 1
Up Type= 0
Dn Type= 3
Dn Slope=0.04649
Boundary for River Rch & Prof#=LFMEADOWCK,Main            , 2
Up Type= 0
Dn Type= 3
Dn Slope=0.04649
Boundary for River Rch & Prof#=LFMEADOWCK,Main            , 3
Up Type= 0
Dn Type= 3
Dn Slope=0.04649
Boundary for River Rch & Prof#=LFMEADOWCK,Main            , 4
Up Type= 0
Dn Type= 3
Dn Slope=0.04649
Boundary for River Rch & Prof#=LFMEADOWCK,Main            , 5
Up Type= 0
Dn Type= 3
Dn Slope=0.04649
Boundary for River Rch & Prof#=LFMEADOWCK,Main            , 6
Up Type= 0
Dn Type= 3
Dn Slope=0.04649
DSS Import GetInterval= 0
DSS Import GetPeak= 0
DSS Import FillOption= 0

--- LFMEADOWCK.g01 (geometry) ---

Geom Title=Geometry
Program Version=5.07

River Reach=LFMEADOWCK      ,Main
Reach XY= 30
     1998336.513305291.6249999131998334.71353765305258.616645626
1998348.57350779305238.4516104541998349.21753951305224.872543888
1998347.89643946305209.4136319621998322.57699319 305171.72359501
1998327.83199999305072.8749999161998346.36085945305041.409833727
1998366.85818946304976.5485668151998354.86025644304928.084540558
1998361.92018946304907.2418495341998361.47089854304873.310648865
     1998376.977304827.1609999191998443.40726465  304714.7284345
1998479.22169774304630.2404901461998507.71494286304588.660150294
1998652.65394348304533.3347693651998682.04130374304508.298055559
 1998684.6416045304449.871792404     1998659.095304395.302999912
1998601.66052782304351.9335472781998512.36973534304305.134924723
     1998465.953304269.4349999161998434.81754662304238.689007141
1998408.89941503304189.8840931551998405.18899999304156.587999911
1998434.81754662303890.8433156191998439.88940583303882.049282803
1998488.64706087303850.2350855681998619.58986661303820.457288592

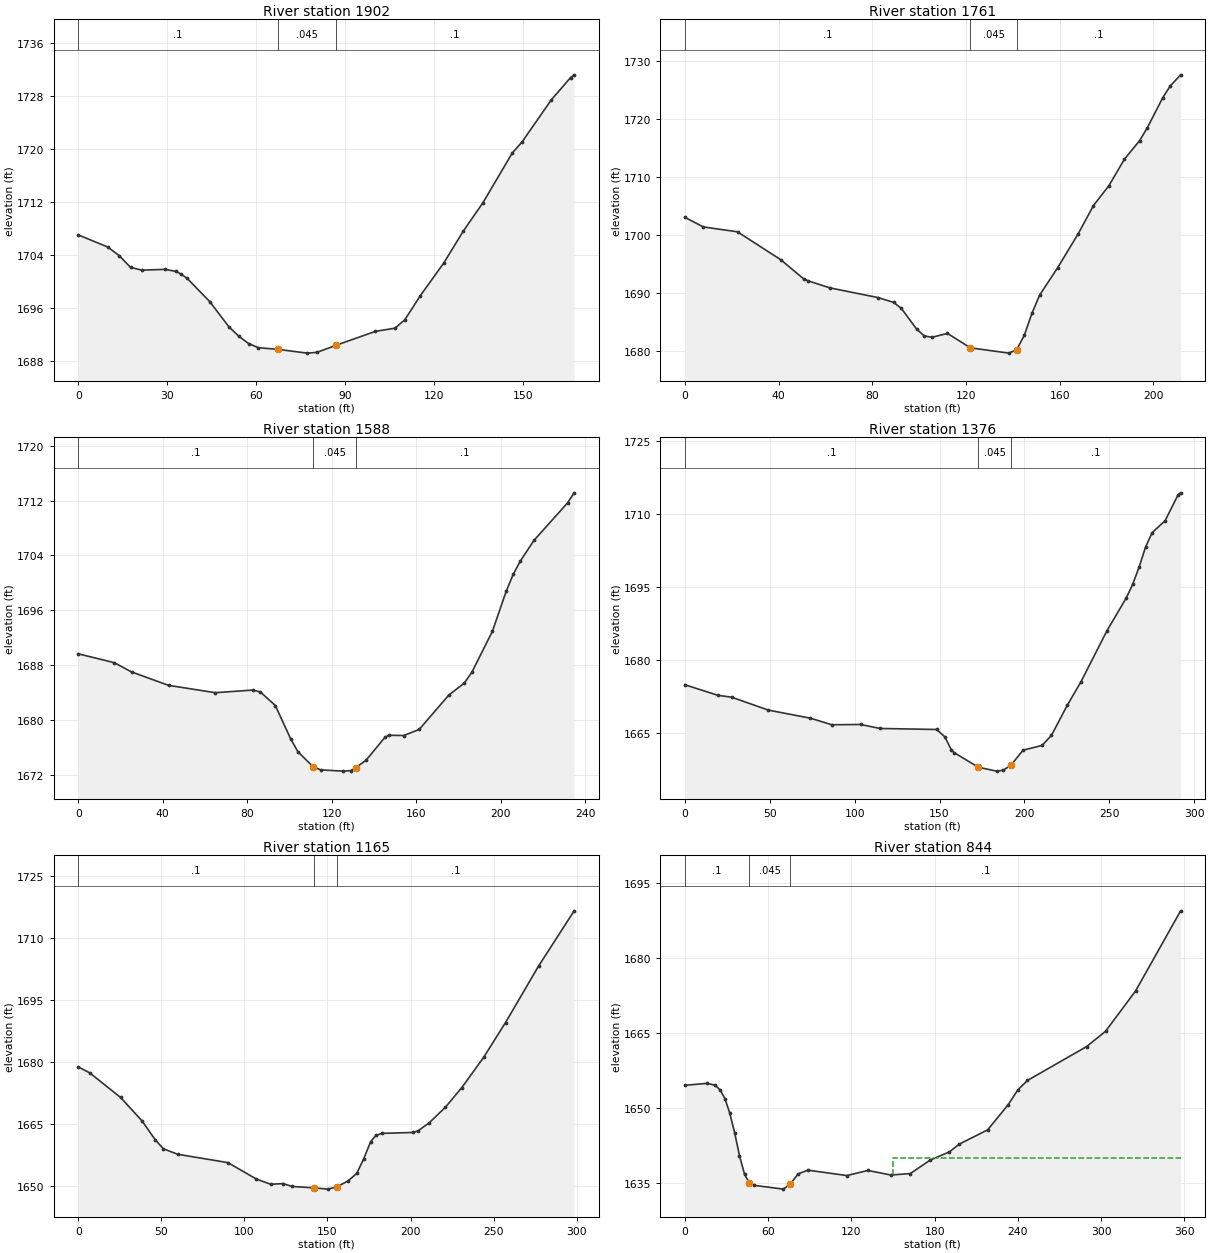
Type RM Length L Ch R = 1 ,1902    ,138.2,141.4,138.2
XS GIS Cut Line= 3
 1998401.1185578305302.8981182111998363.97304504305280.547852059
1998240.57439248305290.621211452
#Sta/Elev= 30
       0 1707.05     9.9 1705.23    13.8 1703.92    17.6 1702.15    21.4 1701.73
    29.1 1701.85    32.9 1701.55    34.6 1701.15    36.7 1700.49    44.3 1696.99
    50.8 1693.16    54.1 1691.76    57.4 1690.65    60.7 1690.02    67.3 1689.77
    77.2  1689.2    80.5 1689.32      87  1690.4   100.2 1692.49   106.8 1692.97
   110.1 1694.24   115.3 1697.86   123.3 1702.86   129.8 1707.62   136.4 1711.89
   146.3  1719.4   149.6 1721.08   159.5 1727.45     166 1730.82   167.2 1731.23
#Mann= 3 ,-1 , 0
       0      .1       0    67.3    .045       0      87      .1       0
Bank Sta=67.3,87
XS Rating Curve= 0 ,0
Exp/Cntr(USF)=0,0
Exp/Cntr=0.3,0.1

Type RM Length L Ch R = 1 ,1761    ,166.5,172.6,179.5
XS GIS Cut Line= 3
1998427.56112621 305209.719543831998373.10202699305152.427312284
1998240.57439248305156.519614537
#Sta/Elev= 30
       0 1703.03     7.9 1701.36    22.5 1700.52    40.9 1695.72    50.7 1692.42
    52.7 1692.06    61.9 1690.86    82.5 1689.18    89.1 1688.36    92.4 1687.33
    98.9 1683.77   102.2 1682.57   105.5 1682.34   112.1 1683.01   121.9 1680.52
   138.3 1679.61   141.6 1680.17   144.9  1682.7   148.2 1686.53   151.4 1689.59
   159.1 1694.32   167.9 1700.19   174.4 1705.04     181 1708.48   187.6 1713.03
   194.1 1716.24   197.4 1718.47     204 1723.66   207.2 1725.67   211.6 1727.58
#Mann= 3 ,-1 , 0
       0      .1       0   121.9    .045       0   141.6      .1       0
Bank Sta=121.9,141.6
XS Rating Curve= 0 ,0
Exp/Cntr(USF)=0,0
Exp/Cntr=0.3,0.1

Type RM Length L Ch R = 1 ,1588    ,211.5,212.7,214.4
XS GIS Cut Line= 4
1998441.65534661305075.6115176831998399.15836167305004.783209454
1998303.77623992 304963.545394441998255.61299033 304966.37852677
#Sta/Elev= 30
       0 1689.64      17 1688.35    25.2    1687    42.7 1685.04    64.8 1683.97
    82.6 1684.35    86.2 1684.08    93.3 1682.09   100.5 1677.27     104 1675.34
   111.2 1673.16   114.8  1672.7   125.5 1672.52   129.1  1672.6   131.4 1673.04
   136.2 1674.09   145.2 1677.45   146.9 1677.75   154.1 1677.72   161.4  1678.6
   175.5 1683.64   182.7 1685.35   186.3 1686.92   196.1 1692.94   202.7 1698.85
     206 1701.27   209.3 1703.18   215.8 1706.21   231.7 1711.68   234.8 1713.14
#Mann= 3 ,-1 , 0
       0      .1       0   111.2    .045       0   131.4      .1       0
Bank Sta=111.2,131.4
XS Rating Curve= 0 ,0
Exp/Cntr(USF)=0,0
Exp/Cntr=0.3,0.1

Type RM Length L Ch R = 1 ,1376    ,208.9,210.3,212.5
XS GIS Cut Line= 3
1998511.44643736304913.2982099841998476.03768093304834.276229152
1998299.42571284304729.345402145
#Sta/Elev= 30
       0 1674.97    19.6 1672.79    27.6 1672.41    49.2 1669.76      74  1668.1
    86.6 1666.75   103.5 1666.81     115 1665.99   148.3 1665.78   153.1 1664.29
   156.9 1661.66   158.5 1661.05   172.9 1658.03   183.6 1657.23   187.5 1657.41
     192 1658.42   199.2 1661.53   210.4 1662.51   215.9 1664.56   225.3 1670.79
   233.3 1675.57   248.5 1685.98     260 1692.81   263.8 1695.62   267.6 1699.18
   271.4 1703.29   275.2 1706.19   282.9 1708.68   290.5 1713.97     292 1714.38
#Mann= 3 ,-1 , 0
       0      .1       0   172.9    .045       0     192      .1       0
Bank Sta=172.9,192
XS Rating Curve= 0 ,0
Exp/Cntr(USF)=0,0
Exp/Cntr=0.3,0.1

Type RM Length L Ch R = 1 ,1165    ,335.6,321.4,289.9
XS GIS Cut Line= 3
1998608.83670447304697.9418350431998456.74218156304568.877397618
1998357.90473134 304574.63491899
#Sta/Elev= 30
       0 1678.79     6.9 1677.34    25.4  1671.4    38.3 1665.74    46.4 1661.08
    51.2 1658.95    59.8 1657.62      90  1655.6   107.2 1651.61   115.8 1650.35
   123.3 1650.51   128.7 1649.82   141.9 1649.48   150.2 1649.17   155.8 1649.72
   162.5  1651.2   167.6 1652.99   171.7 1656.42     176 1660.68   179.1 1662.17
   182.8 1662.69   201.3  1662.9   204.6 1663.32   211.1  1665.2     221 1669.02
   230.9  1673.8     244 1681.11   257.2 1689.56   277.1 1703.26   298.5 1716.63
#Mann= 3 ,-1 , 0
       0      .1       0   141.9    .045       0   155.8      .1       0
Bank Sta=141.9,155.8
XS Rating Curve= 0 ,0
Exp/Cntr(USF)=0,0
Exp/Cntr=0.3,0.1

Type RM Length L Ch R = 1 ,844     ,238.7,233,218.6
XS GIS Cut Line= 2
1998714.82445919304383.5620158771998381.46397174304512.242618544
#Sta/Elev= 30
       0  1654.5    16.2 1654.89    21.9  1654.5    25.4  1653.6    28.9 1651.85
    32.4 1648.93    35.9 1645.01    39.4 1640.41    43.1 1636.63    46.5 1634.96
      50 1634.45    71.1 1633.69    76.1 1634.75    81.6 1636.73    88.7 1637.49
   116.8 1636.41   131.9 1637.43   148.5 1636.52   162.5 1636.81   176.6 1639.47
   190.7 1641.16   197.7  1642.7   218.2 1645.56   232.9 1650.56   239.9 1653.54
   246.9 1655.47   289.5 1662.25   303.2 1665.33   324.8 1673.39   357.3 1689.47
#Mann= 3 ,-1 , 0
       0      .1       0    46.5    .045       0    76.1      .1       0
#XS Ineff= 2 , 0
                             150            1640
Permanent Ineff=
       F       F
Bank Sta=46.5,76.1
XS Rating Curve= 0 ,0
Exp/Cntr(USF)=0,0
Exp/Cntr=0.3,0.1

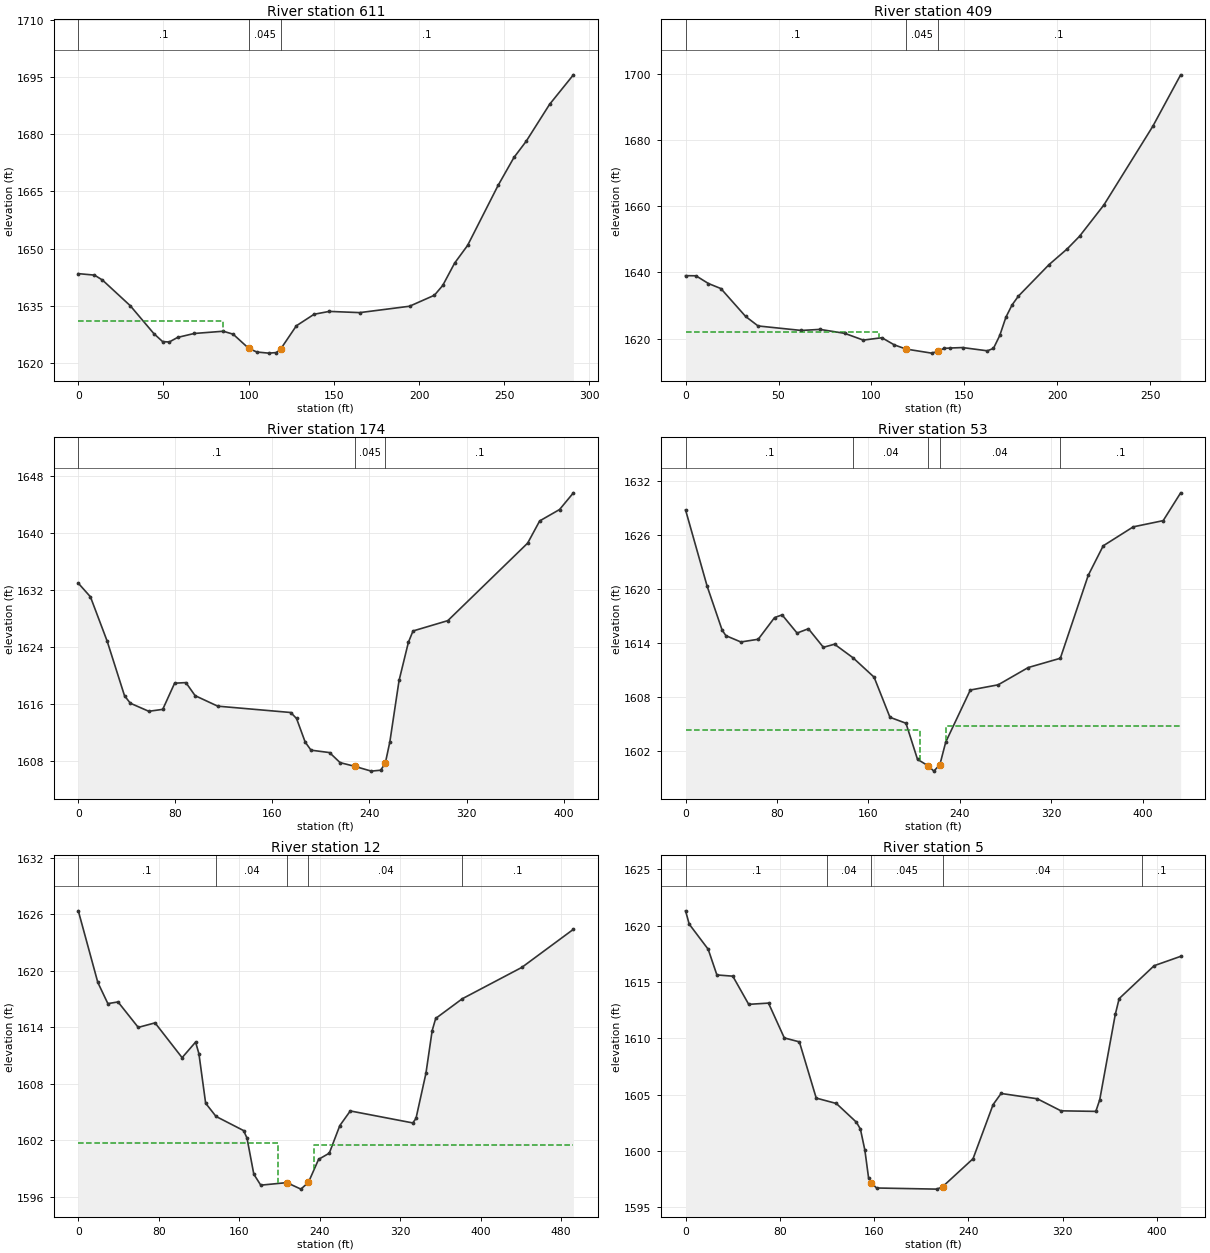
Type RM Length L Ch R = 1 ,611     ,184.9,201.6,213.2
XS GIS Cut Line= 2
1998546.76703057304192.1072524651998350.70328837304406.533459944
#Sta/Elev= 30
       0 1643.44     9.5 1643.05    14.2 1641.75    30.5 1635.03    44.4 1627.69
    49.5 1625.62    53.4 1625.52    58.3 1626.72      68 1627.75    85.1 1628.34
    90.9 1627.56   100.1 1623.82   104.8 1622.89   111.7  1622.6   116.2 1622.74
   118.7 1623.62     128 1629.77   138.4 1632.79   147.3 1633.54   165.2 1633.22
   194.4 1634.89     209 1637.77   213.9 1640.34   220.9 1646.21   228.5 1650.84
   246.4 1666.57   255.7 1673.89   262.9 1678.15   276.6 1687.81   290.6 1695.56
#Mann= 3 ,-1 , 0
       0      .1       0   100.1    .045       0   118.7      .1       0
#XS Ineff= 2 , 0
              85    1631
Permanent Ineff=
       F       F
Bank Sta=100.1,118.7
XS Rating Curve= 0 ,0
Exp/Cntr(USF)=0,0
Exp/Cntr=0.3,0.1

Type RM Length L Ch R = 1 ,409     ,228.1,235.2,258.4
XS GIS Cut Line= 3
1998542.49825878304118.6962915721998361.24295246304086.176957202
1998279.14496077304089.908684097
#Sta/Elev= 30
       0 1639.04     5.6    1639    12.3 1636.67      19 1635.15    32.3 1626.74
      39 1623.87    62.3 1622.51    72.3 1622.83    85.6 1621.64    95.6  1619.6
   105.6 1620.32   112.3 1618.15   118.6  1616.9   132.3 1615.67   135.6 1616.21
     139  1617.1   142.3 1617.21     149 1617.35   162.3 1616.37   165.6 1617.09
     169 1620.99   172.3  1626.5   175.6 1630.19     179 1632.85   195.5 1642.37
   205.3 1647.13   211.9 1650.92     225 1660.36   251.3 1684.09   266.3 1699.63
#Mann= 3 , 0 , 0
       0      .1       0   118.6    .045       0   135.6      .1       0
#XS Ineff= 2 , 0
             104    1622
Permanent Ineff=
       F       F
Bank Sta=118.6,135.6
XS Rating Curve= 0 ,0
Exp/Cntr(USF)=0,0
Exp/Cntr=0.3,0.1

Type RM Length L Ch R = 1 ,174     ,119.6,121.2,128.2
XS GIS Cut Line= 3
1998572.88517778304068.5845304121998421.48368662303814.827101562
1998308.99877593303820.691243825
#Sta/Elev= 30
       0 1632.97      10 1631.06    23.8 1624.84    38.1 1617.19    42.9 1616.14
    58.1 1615.01    69.6 1615.28    79.4 1618.95    88.7 1619.03    96.3  1617.2
   114.9 1615.73   175.1 1614.84   179.9    1614     187  1610.7   191.8 1609.56
   207.1 1609.22   215.8 1607.81   227.7  1607.3   241.5 1606.62   249.2 1606.75
     253 1607.69   256.8 1610.72   264.4 1619.33   272.1 1624.69   275.9 1626.27
   304.6 1627.72   370.4 1638.59   380.3  1641.7   396.7  1643.3   408.1 1645.64
#Mann= 3 ,-1 , 0
       0      .1       0   227.7    .045       0     253      .1       0
Bank Sta=227.7,253
XS Rating Curve= 0 ,0
Exp/Cntr(USF)=0,0
Exp/Cntr=0.5,0.3

Type RM Length L Ch R = 1 ,53      ,63.7,41,41.6
XS GIS Cut Line= 4
1998598.55435168304044.077272328 1998595.7047796303909.073236826
1998555.04327252303795.6207153731998377.29974402303799.966581865
#Sta/Elev= 30
       0 1628.76    18.9 1620.28      32 1615.41    35.3 1614.79    48.4 1614.09
    63.6 1614.39    77.9  1616.8    84.5  1617.1    97.6 1615.08   107.5 1615.56
   120.6  1613.5   130.4 1613.84   146.6 1612.33     165 1610.18   178.9 1605.72
   192.9 1605.06     203 1601.05   212.51600.314   217.3 1599.74   222.6 1600.47
   227.7 1602.97   249.2 1608.75   273.6 1609.33   299.9 1611.25     328 1612.28
   352.4 1621.49   365.5 1624.77   391.8 1626.88     418 1627.57   433.3 1630.66
#Mann= 5 ,-1 , 0
       0      .1       0   146.6     .04       0   212.5    .045       0
   222.6     .04       0     328      .1       0
#XS Ineff= 2 , 0
       0     205  1604.3     228       0  1604.7
Permanent Ineff=
       F       F
Bank Sta=212.5,222.6
XS Rating Curve= 0 ,0
Exp/Cntr(USF)=0,0
Exp/Cntr=0.5,0.3

Type RM Length L Ch R = 1 ,12      ,14.7,7.4,8.2
XS GIS Cut Line= 4
1998608.26674934304034.318263265 1998634.1094631303910.961991752
1998581.41483925303733.7426653281998400.48202785303744.516628162
#Sta/Elev= 30
       0 1626.35    19.4 1618.76    29.4 1616.51    39.5 1616.69    59.6 1613.99
    76.3 1614.47   103.2 1610.78   116.6 1612.43   119.9 1611.21   126.6 1605.95
   136.9 1604.55   164.3 1603.05   167.7 1602.26   174.5 1598.42   181.4 1597.26
   207.3 1597.53   221.3 1596.84   228.81597.563   238.9    1600   249.5 1600.65
     260 1603.58   270.4 1605.13   332.5 1603.86   335.7 1604.33   345.6 1609.12
   351.8 1613.65   355.3 1614.94   381.8 1617.03   440.9 1620.35   492.2 1624.39
#Mann= 5 ,-1 , 0
       0      .1       0   136.9     .04       0   207.3    .045       0
   228.8     .04       0   381.8      .1       0
#XS Ineff= 2 , 0
          198.76 1601.75  234.25         1601.51
Permanent Ineff=
       F       F
Bank Sta=207.3,228.8
XS Rating Curve= 0 ,0
Exp/Cntr(USF)=0,0
Exp/Cntr=0.5,0.3

Type RM Length L Ch R = 1 ,5       ,,,
XS GIS Cut Line= 4
1998621.29276925304018.3992311021998643.42268113303920.845039152
1998583.73802546303711.5080348061998481.74525943303721.140684931
#Sta/Elev= 30
       0 1621.33     3.1 1620.15    19.2 1617.92    26.6 1615.64    40.1 1615.53
    53.6 1613.03    70.4 1613.14    83.8 1610.05    96.6  1609.7   110.9 1604.71
     128 1604.23     145 1602.57   148.4 1601.96   152.2 1600.08   155.3 1597.65
   157.5 1597.21   162.1 1596.73   213.3 1596.63   218.1 1596.84     244 1599.33
     261 1604.13   267.8 1605.12   298.5 1604.65   318.6 1603.58   348.2 1603.53
   351.5 1604.55   364.7 1612.13     368 1613.54   397.7 1616.46   420.2 1617.29
#Mann= 5 ,-1 , 0
       0      .1       0  120.03     .04       0   157.5    .045       0
   218.1     .04       0  387.71      .1       0
Bank Sta=157.5,218.1
XS Rating Curve= 0 ,0
Exp/Cntr(USF)=0,0
Exp/Cntr=0.3,0.1
LCMann Table=0

Chan Stop Cuts=-1
Use User Specified Reach Order=0
Composite Channel Slope=5